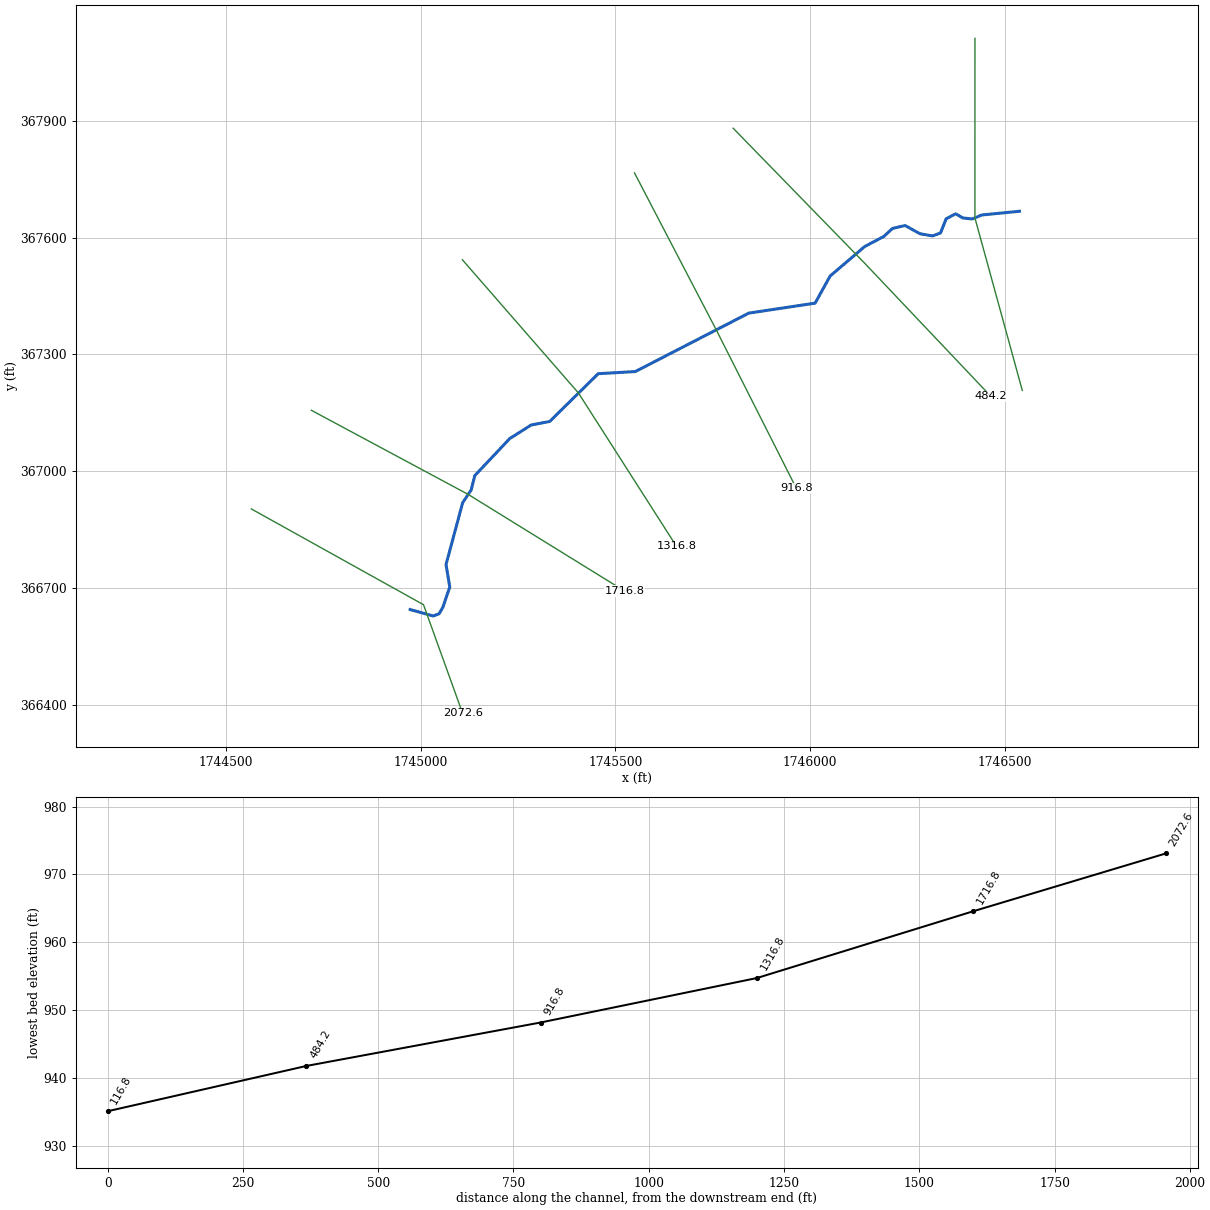
--- EstRn.prj (project) ---

Proj Title=EstRn
Current Plan=p01
Default Exp/Contr=0,0
English Units
Geom File=g01
Flow File=f01
Plan File=p01
BEGIN DESCRIPTION:
END DESCRIPTION:
DSS Export Rating Curves= 0
DSS Export Rating Curve Sorted= 0
DSS Export Volume Flow Curves= 0
DXF OffsetX= 0
DXF OffsetY= 0
DXF ScaleX= 0
DXF ScaleY= 0

--- EstRn.p01 (plan) ---

Plan Title=Floodplain
Program Version=4.00
Geom File=g01
Flow File=f01
K Sum by GR=0
Std Step Tol=0.01
Critical Tol=0.01
Num of Std Step Trials=20
Max Error Tol=0.3
Flow Tol Ratio=0.001
Split Flow NTrial=30
Split Flow Tol=0.02
Split Flow Ratio=0.02
Log Output Level=0
Friction Slope Method=1
Unsteady Friction Slope Method=2
Unsteady Bridges Friction Slope Method=1
Global Log Level=0
CheckData=False
Run HTab=0
Run UNet=0
Run PostProcess=0
UNET Theta=0
UNET Theta Warmup=0
UNET ZTol=0
UNET ZSATol=0
UNET MxIter=0
UNET MaxInSteps=0
UNET DtIC=0
UNET DtMin=0
UNET MaxCRTS=0
UNET WFStab=0
UNET SFStab=0
UNET WFX=0
UNET SFX=0
UNET DSS MLevel=0
UNET DZMax Abort=0
UNET Convert EG Bridges=0
UNET Use Existing IB Tables=0
UNET Froude Limit=0
UNET Froude Power=0
Write IC File=0
Echo Input=False
Echo Output=False
Write Detailed=0

--- EstRn.f01 (steady flow) ---

Flow Title=NFF Regression Equation
Program Version=4.00
Number of Profiles=1
Profile Names=P100yr
River Rch & RM=EstRn,Main      ,2072.6
747.4272
River Rch & RM=EstRn,Main      ,116.8
800.5936
Boundary for River Rch & Prof#=EstRn,Main      ,1
Up Type=0
Dn Type=3
Dn Slope=0.016174

--- EstRn.g01 (geometry) ---

Geom Title=USGS 3m DEM
Program Version=4.00

River Reach=EstRn     ,Main
Reach XY= 30
     1744973.033      366644.667     1745032.171      366628.164
     1745047.299      366633.665     1745056.926      366650.168
     1745074.805      366702.430     1745065.178      366760.193
     1745107.904      366919.184     1745129.878      366952.146
     1745139.035      366988.770     1745228.763      367083.993
     1745283.700      367118.786     1745331.311      367127.942
     1745455.833      367250.633     1745551.056      367256.126
     1745842.217      367406.285     1746012.519      367431.922
     1746050.975      367501.508     1746139.815      367577.432
     1746188.619      367603.139     1746211.032      367623.826
     1746243.452      367631.357     1746281.723      367610.138
     1746314.028      367604.604     1746334.341      367612.303
     1746348.802      367648.691     1746373.181      367661.545
     1746391.299      367650.944     1746415.587      367648.106
     1746439.943      367658.395     1746536.961      367667.987

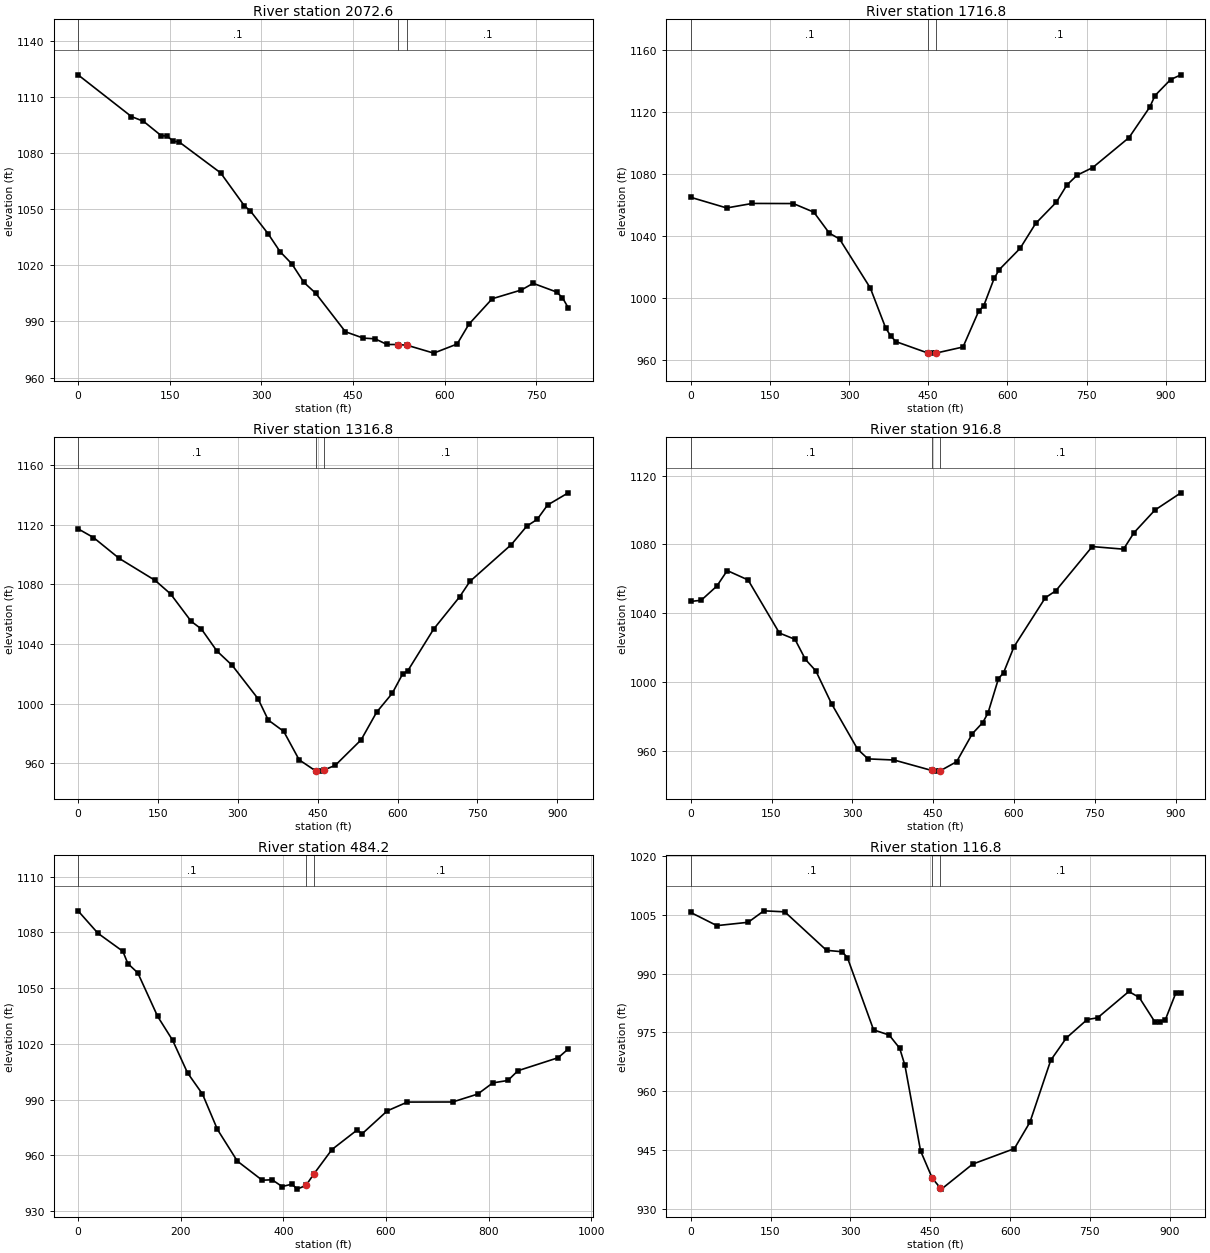
Type RM Length L Ch R = 1 ,2072.6,344.936,355.868,370.021
XS GIS Cut Line= 3
     1744565.574      366903.160     1745007.415      366657.045
     1745107.812      366377.858
#Sta/Elev= 30
       0 1121.75    87.5 1099.43   107.0 1096.96   136.2 1089.24   145.9 1089.09
   155.6 1086.26   165.3 1085.94   233.4 1069.38   272.3 1051.79   282.1 1049.05
   311.2 1036.83   330.7 1027.31   350.1 1020.73   369.6 1010.92   389.0 1005.09
   437.7  984.51   466.9  981.12   486.3  980.73   505.8  977.70   524.2  977.69
   539.2  977.26   582.3  973.09   620.6  977.95   639.8  988.51   678.0 1002.14
   725.9 1006.84   745.0 1010.38   783.3 1005.75   792.9 1002.77   802.5  997.32
#Mann= 3 , 0 , 0
       0     0.1       0   524.2   0.045       0   539.2     0.1       0
Bank Sta=   524.2,   539.2
Exp/Cntr=0.3,0.1

Type RM Length L Ch R = 1 ,1716.8,408.05,400,389.943
XS GIS Cut Line= 3
     1744719.519      367156.646     1745122.094      366940.470
     1745523.292      366692.259
#Sta/Elev= 30
       0 1064.99    68.1 1058.13   116.7 1061.04   194.4 1060.96   233.3 1055.41
   262.5 1041.92   281.9 1038.14   340.3 1006.50   369.4  980.73   379.2  975.50
   388.9  971.97   449.4  964.62   456.9  964.57   464.4  964.57   515.9  968.52
   545.4  991.49   555.2  995.14   574.9 1012.76   584.7 1018.44   624.0 1032.06
   653.5 1048.14   692.8 1061.88   712.5 1072.84   732.1 1079.26   761.6 1084.14
   830.4 1103.47   869.7 1123.12   879.6 1130.53   909.1 1140.84   928.7 1143.92
#Mann= 3 , 0 , 0
       0     0.1       0   449.4   0.045       0   464.4     0.1       0
Bank Sta=   449.4,   464.4
Exp/Cntr=0.3,0.1

Type RM Length L Ch R = 1 ,1316.8,405.911,400,397.202
XS GIS Cut Line= 3
     1745107.144      367543.422     1745405.035      367201.104
     1745656.214      366807.694
#Sta/Elev= 30
       0 1117.38    29.0 1111.51    77.2 1097.53   144.8 1082.73   173.8 1073.65
   212.4 1055.28   231.7 1050.08   260.7 1035.38   289.6 1025.66   337.9 1003.36
   357.2  988.99   386.2  981.40   415.2  962.31   446.3  954.84   453.8  954.72
   461.3  955.43   483.0  958.60   531.6  975.73   560.7  994.29   589.9 1006.91
   609.4 1019.84   619.1 1022.03   667.7 1050.03   716.3 1071.60   735.8 1082.03
   813.6 1106.78   842.7 1119.17   862.2 1123.72   881.6 1133.31   920.5 1141.53
#Mann= 3 , 0 , 0
       0     0.1       0   446.3   0.045       0   461.3     0.1       0
Bank Sta=   446.3,   461.3
Exp/Cntr=0.3,0.1

Type RM Length L Ch R = 1 ,916.8,424.236,432.536,440.79
XS GIS Cut Line= 3
     1745548.870      367766.548     1745758.885      367362.925
     1745963.925      366956.696
#Sta/Elev= 30
       0 1046.84    19.4 1047.50    48.4 1055.72    67.8 1064.78   106.5 1059.32
   164.6 1028.47   193.6 1024.79   213.0 1013.10   232.3 1006.44   261.4  987.40
   309.8  960.92   329.1  955.28   377.5  954.62   447.5  948.54   455.0  948.16
   462.5  948.22   493.7  953.65   522.8  969.91   542.1  976.38   551.8  981.88
   571.2 1001.84   580.9 1005.49   600.2 1020.51   658.3 1048.99   677.7 1053.01
   745.4 1078.74   803.5 1077.23   822.9 1086.80   861.6 1099.92   910.0 1109.99
#Mann= 3 , 0 , 0
       0     0.1       0   447.5   0.045       0   462.5     0.1       0
Bank Sta=   447.5,   462.5
Exp/Cntr=0.3,0.1

Type RM Length L Ch R = 1 ,484.2,386.728,367.464,354.21
XS GIS Cut Line= 3
     1745802.043      367881.426     1746140.125      367533.971
     1746463.307      367192.632
#Sta/Elev= 30
       0 1091.65    38.8 1079.55    87.3 1069.85    97.0 1063.25   116.4 1058.22
   155.1 1034.76   184.2 1021.96   213.3 1004.37   242.4  992.96   271.5  973.91
   310.3  956.85   358.7  946.56   378.1  946.80   397.5  943.15   416.9  944.45
   426.6  941.76     444  943.75     459  949.78   494.6  963.09   543.6  973.60
   553.3  971.54   602.3  983.91   641.5  988.65   729.6  988.69   778.6  992.96
   808.0  998.99   837.3 1000.27   856.9 1005.53   935.3 1012.54   954.9 1017.24
#Mann= 3 , 0 , 0
       0     0.1       0     444   0.045       0     459     0.1       0
Bank Sta=     444,     459
Exp/Cntr=0.3,0.1

Type RM Length L Ch R = 1 ,116.8,116.58,116.772,110.44
XS GIS Cut Line= 3
     1746422.673      368112.312     1746422.544      367651.045
     1746544.135      367207.756
#Sta/Elev= 30
       0 1005.60    49.1 1002.24   108.0 1003.09   137.4 1006.01   176.7 1005.75
   255.2  995.94   284.6  995.58   294.4  994.07   343.5  975.68   372.9  974.34
   392.6  970.98   402.4  966.64   431.8  944.83   453.8  937.87   468.8  935.40
   471.0  935.08   529.7  941.46   608.0  945.40   637.3  952.15   676.4  967.94
   705.8  973.62   744.9  978.31   764.4  978.74   823.1  985.45   842.7  983.92
   872.0  977.69   881.8  977.69   891.6  978.23   911.1  984.98   920.9  985.13
#Mann= 3 , 0 , 0
       0     0.1       0   453.8   0.045       0   468.8     0.1       0
Bank Sta=   453.8,   468.8
Exp/Cntr=0.3,0.1